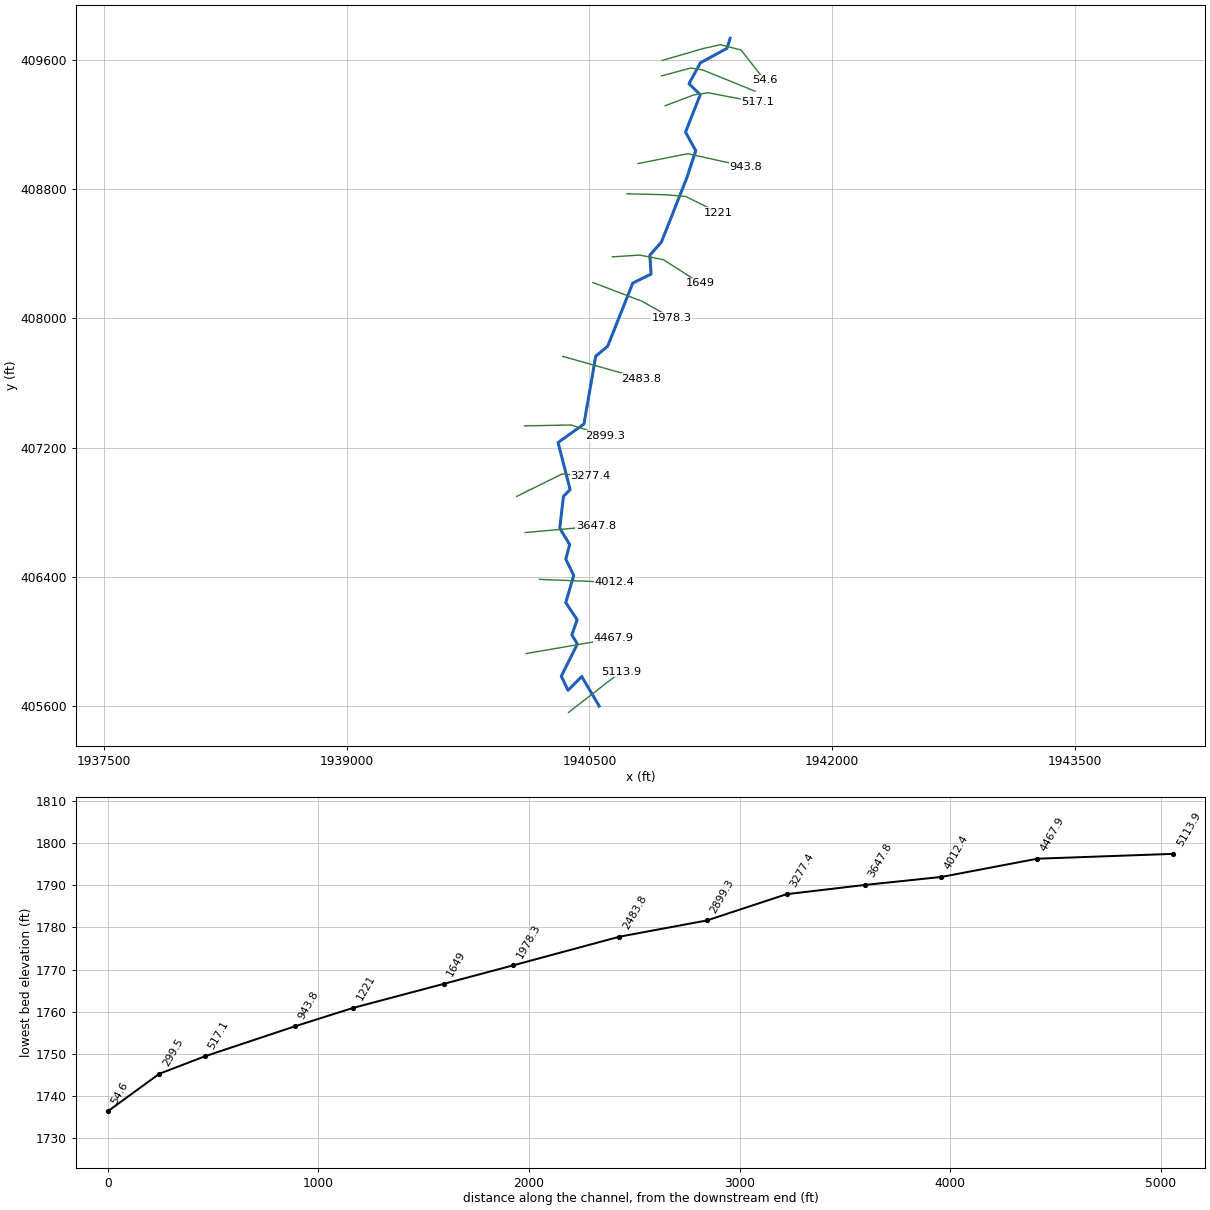
--- GLADERN3.prj (project) ---

Proj Title=GLADERN3
Current Plan=p01
Default Exp/Contr=0,0
English Units
Geom File=g01
Flow File=f01
Plan File=p01
BEGIN DESCRIPTION:
END DESCRIPTION:
DSS Export Rating Curves= 0
DSS Export Rating Curve Sorted= 0
DSS Export Volume Flow Curves= 0
DXF OffsetX= 0
DXF OffsetY= 0
DXF ScaleX= 0
DXF ScaleY= 0

--- GLADERN3.p01 (plan) ---

Plan Title=Floodplain
Program Version=4.00
Geom File=g01
Flow File=f01
K Sum by GR=0
Std Step Tol=0.01
Critical Tol=0.01
Num of Std Step Trials=20
Max Error Tol=0.3
Flow Tol Ratio=0.001
Split Flow NTrial=30
Split Flow Tol=0.02
Split Flow Ratio=0.02
Log Output Level=0
Friction Slope Method=1
Unsteady Friction Slope Method=2
Unsteady Bridges Friction Slope Method=1
Global Log Level=0
CheckData=False
Run HTab=0
Run UNet=0
Run PostProcess=0
UNET Theta=0
UNET Theta Warmup=0
UNET ZTol=0
UNET ZSATol=0
UNET MxIter=0
UNET MaxInSteps=0
UNET DtIC=0
UNET DtMin=0
UNET MaxCRTS=0
UNET WFStab=0
UNET SFStab=0
UNET WFX=0
UNET SFX=0
UNET DSS MLevel=0
UNET DZMax Abort=0
UNET Convert EG Bridges=0
UNET Use Existing IB Tables=0
UNET Froude Limit=0
UNET Froude Power=0
Write IC File=0
Echo Input=False
Echo Output=False
Write Detailed=0

--- GLADERN3.f01 (steady flow) ---

Flow Title=NFF Regression Equation
Program Version=4.00
Number of Profiles=1
Profile Names=P100yr
River Rch & RM=GLADERN3,Main      ,5113.9
516.8631
River Rch & RM=GLADERN3,Main      ,2483.8
573.6105
River Rch & RM=GLADERN3,Main      ,299.5
604.0772
Boundary for River Rch & Prof#=GLADERN3,Main      ,1
Up Type=0
Dn Type=3
Dn Slope=0.024006

--- GLADERN3.g01 (geometry) ---

Geom Title=USGS 10m DEM
Program Version=4.10

River Reach=GLADERN3        ,Main
Reach XY= 30
     1940559.734      405601.917     1940451.956      405784.988
     1940367.443      405699.258     1940325.781      405786.216
     1940424.829      405985.726     1940391.258       406042.38
     1940423.646      406136.359     1940353.215      406241.802
     1940402.696      406410.401     1940353.668      406510.425
     1940377.539      406601.571     1940316.166      406702.037
     1940339.109      406899.354     1940380.438       406940.83
     1940305.708      407232.647     1940465.864      407347.231
     1940538.492      407766.386     1940612.116      407828.348
     1940767.756       408219.34     1940880.604      408274.896
     1940872.791      408391.215      1940944.84       408473.68
     1941101.706       408871.61     1941156.645      409037.917
     1941093.277      409153.368     1941184.423      409384.271
     1941114.979      409452.847     1941185.291      409582.187
     1941349.354      409671.597     1941369.098       409733.82

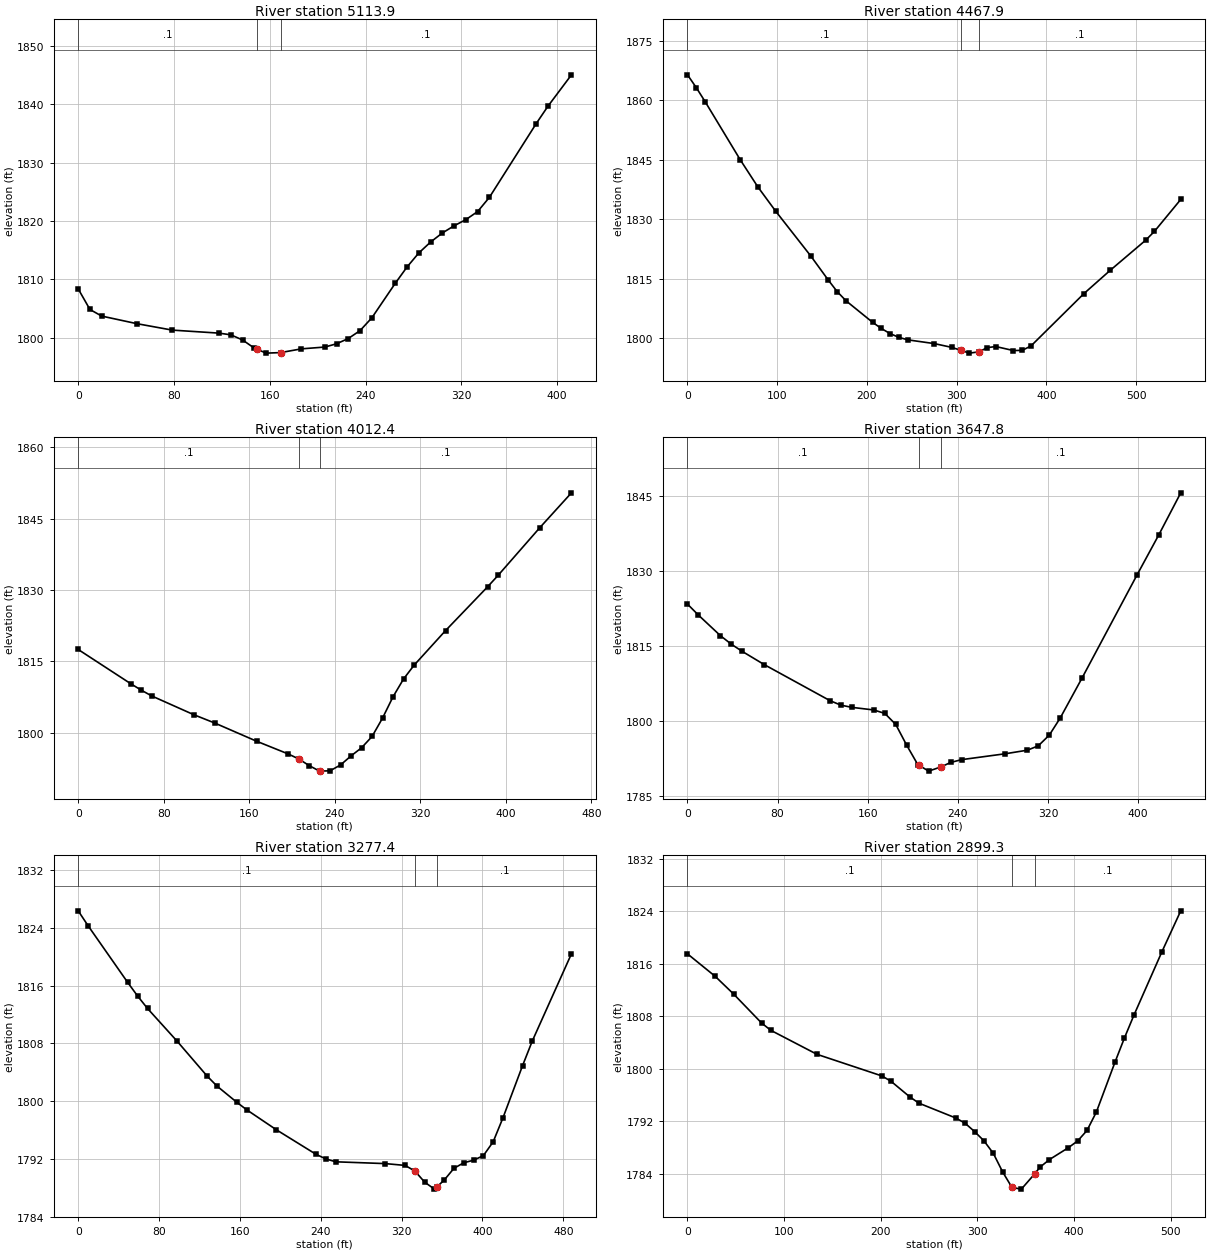
Type RM Length L Ch R = 1 ,5113.9  ,583.3,646,571.6
XS GIS Cut Line= 2
     1940370.743      405562.761     1940696.264      405815.365
#Sta/Elev= 30
       0 1808.39     9.8 1804.87    19.6 1803.74      49 1802.44    78.5 1801.34
   117.7 1800.82   127.5 1800.53   137.3 1799.65   147.2 1798.24     149 1798.09
     157  1797.4     169 1797.49   186.4 1798.13     206 1798.44   215.8    1799
   225.6  1799.9   235.4 1801.25   245.3 1803.45   264.9 1809.37   274.7 1812.15
   284.5 1814.54   294.3  1816.4   304.1 1817.95   313.9 1819.18   323.7 1820.23
   333.6 1821.62   343.4 1824.04   382.6 1836.69   392.4 1839.66     412 1845.02
#Mann= 3 , 0 , 0
       0      .1       0     149    .045       0     169      .1       0
Bank Sta=149,169
XS Rating Curve= 0 ,0
Exp/Cntr=0.3,0.1

Type RM Length L Ch R = 1 ,4467.9  ,461.4,455.5,445.4
XS GIS Cut Line= 2
     1940108.331      405926.708     1940650.048      406020.184
#Sta/Elev= 30
       0 1866.42     9.8 1863.19    19.6 1859.68    58.9 1844.96    78.5 1838.13
    98.2 1832.06   137.4 1820.74   157.1 1814.61   166.9 1811.74   176.7 1809.44
   206.2 1804.03     216 1802.47   225.8 1801.17   235.6 1800.23   245.4  1799.6
   274.9 1798.66   294.5  1797.7   305.1 1796.93   314.1 1796.25   325.1 1796.58
   333.8 1797.63   343.6 1797.91   363.2  1796.9     373 1796.95   382.8 1798.06
   441.7 1811.24   471.2 1817.15   510.5  1824.7   520.3 1826.93   549.7    1835
#Mann= 3 , 0 , 0
       0      .1       0   305.1    .045       0   325.1      .1       0
Bank Sta=305.1,325.1
XS Rating Curve= 0 ,0
Exp/Cntr=0.3,0.1

Type RM Length L Ch R = 1 ,4012.4  ,361.4,364.7,367.2
XS GIS Cut Line= 2
     1940191.055      406385.677     1940651.993      406367.448
#Sta/Elev= 25
       0  1817.5    49.1 1810.31    58.9 1808.96    68.7 1807.74     108  1803.8
   127.6 1802.05   166.8 1798.22   196.3 1795.55   206.1 1794.51   215.9 1793.11
   225.7 1791.93   235.6    1792   245.4 1793.24   255.2 1795.14     265 1796.84
   274.8 1799.21   284.6 1803.07   294.4 1807.55   304.3 1811.31   314.1 1814.19
   343.5 1821.46   382.8 1830.66   392.6 1833.06   431.8 1843.13   461.3 1850.43
#Mann= 3 , 0 , 0
       0      .1       0   206.1    .045       0   225.7      .1       0
Bank Sta=206.1,225.7
XS Rating Curve= 0 ,0
Exp/Cntr=0.3,0.1

Type RM Length L Ch R = 1 ,3647.8  ,372.6,370.4,364.5
XS GIS Cut Line= 2
      1940101.82      406675.406     1940538.018      406714.468
#Sta/Elev= 28
       0 1823.37     9.7 1821.18    29.2 1817.08    38.9 1815.37    48.7 1813.92
    68.1  1811.3   126.5  1804.1   136.2  1803.2     146 1802.76   165.4 1802.24
   175.2 1801.55   184.9 1799.34   194.6  1795.2   204.4 1791.35   205.2 1791.24
   214.1 1790.03   225.2 1790.89   233.6 1791.76   243.3 1792.32   282.2  1793.5
   301.7 1794.21   311.4 1795.08   321.2 1797.22   330.9 1800.64   350.4 1808.67
     399 1829.16   418.5 1837.24   437.9 1845.59
#Mann= 3 , 0 , 0
       0      .1       0   205.2    .045       0   225.2      .1       0
Bank Sta=205.2,225.2
XS Rating Curve= 0 ,0
Exp/Cntr=0.3,0.1

Type RM Length L Ch R = 1 ,3277.4  ,383.5,378.1,372.2
XS GIS Cut Line= 3
     1940049.737       406898.93     1940330.958      407038.152
     1940504.569      407022.961
#Sta/Elev= 30
       0 1826.35     9.8 1824.28      49 1816.44    58.8 1814.56    68.6 1812.84
    98.1 1808.28   127.5  1803.5   137.3 1802.11   156.9 1799.87   166.7 1798.83
   196.1 1796.06   235.4 1792.66   245.2 1792.02     255 1791.63     304 1791.38
   323.5 1791.13   333.2 1790.35   342.8 1788.82   352.5 1787.85  355.19 1788.19
   362.2 1789.11   371.9 1790.74   381.6  1791.5   391.2 1791.85   400.9 1792.48
   410.6 1794.39   420.3 1797.71   439.7 1804.93   449.3 1808.33   488.1 1820.41
#Mann= 3 , 0 , 0
       0      .1       0   333.2    .045       0  355.19      .1       0
Bank Sta=333.2,355.19
XS Rating Curve= 0 ,0
Exp/Cntr=0.3,0.1

Type RM Length L Ch R = 1 ,2899.3  ,415.2,415.5,414.9
XS GIS Cut Line= 3
     1940098.753      407335.461     1940385.951      407341.135
     1940598.782      407274.364
#Sta/Elev= 30
       0 1817.48    28.7 1814.05    47.9 1811.33    76.6 1806.95    86.2 1805.83
     134 1802.17   201.1 1798.88   210.6 1798.06   229.8 1795.71   239.4 1794.73
   277.7 1792.46   287.2 1791.67     297  1790.4   306.6 1789.01   316.4 1787.08
     326 1784.26   335.7 1781.88   345.4 1781.63   359.1 1783.94   364.8 1784.99
   374.5 1786.14   393.9 1787.93   403.6 1788.97   413.3 1790.57     423 1793.38
   442.4 1801.03   452.1 1804.69   461.8 1808.12   490.9 1817.83   510.3 1824.04
#Mann= 3 , 0 , 0
       0      .1       0   335.7    .045       0   359.1      .1       0
Bank Sta=335.7,359.1
XS Rating Curve= 0 ,0
Exp/Cntr=0.3,0.1

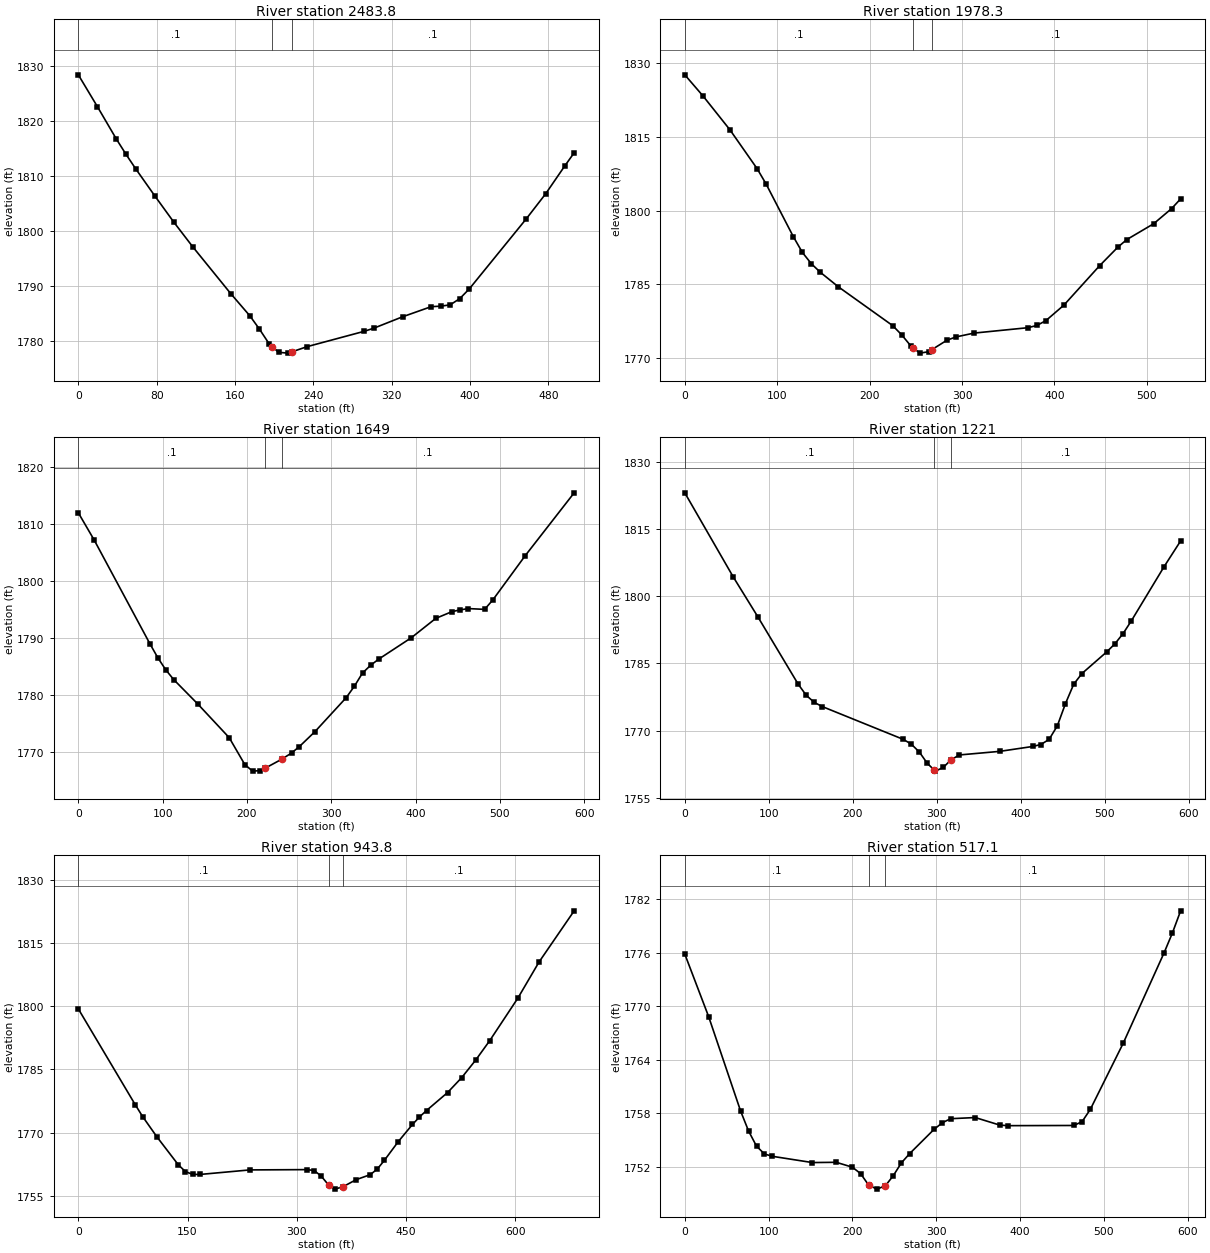
Type RM Length L Ch R = 1 ,2483.8  ,507.6,505.5,502.1
XS GIS Cut Line= 2
     1940334.285      407765.886     1940821.264      407627.865
#Sta/Elev= 29
       0 1828.34    19.5 1822.55    38.9 1816.65    48.7 1813.89    58.4 1811.31
    77.9 1806.39    97.3 1801.62   116.8  1797.1   155.7 1788.57   175.2 1784.54
   184.9 1782.14   194.7  1779.5     198 1778.97   204.4 1777.93   214.1 1777.78
     218 1778.01   233.6 1778.96     292 1781.75   301.8 1782.32     331 1784.38
   360.2 1786.22   369.9 1786.31   379.6 1786.55   389.4 1787.68   399.1 1789.44
   457.5 1802.22     477  1806.7   496.4 1811.73   506.2 1814.18
#Mann= 3 , 0 , 0
       0      .1       0     198    .045       0     218      .1       0
Bank Sta=198,218
XS Rating Curve= 0 ,0
Exp/Cntr=0.3,0.1

Type RM Length L Ch R = 1 ,1978.3  ,323.2,329.3,334.2
XS GIS Cut Line= 3
     1940520.657      408222.715     1940822.306      408107.697
     1941008.938      408003.531
#Sta/Elev= 30
       0 1827.66    19.6 1823.38    48.9 1816.45    78.3 1808.54      88 1805.42
   117.4 1794.72   127.2  1791.5     137 1789.18   146.7 1787.44   166.3 1784.47
     225 1776.58   234.8 1774.69   244.6 1772.45   247.3 1772.04   254.4 1770.98
   264.1 1771.27   267.3 1771.68   283.7 1773.61   293.5 1774.28     313 1775.06
   371.4 1776.16   381.1 1776.62   390.8  1777.6   410.3 1780.76   449.1 1788.82
   468.6 1792.55   478.3  1794.1   507.4 1797.33   526.8 1800.41   536.6  1802.4
#Mann= 3 , 0 , 0
       0      .1       0   247.3    .045       0   267.3      .1       0
Bank Sta=247.3,267.3
XS Rating Curve= 0 ,0
Exp/Cntr=0.3,0.1

Type RM Length L Ch R = 1 ,1649    ,425.3,427.9,430.3
XS GIS Cut Line= 4
     1940641.288      408381.468     1940810.559      408392.318
     1940955.958      408364.106     1941183.823      408218.707
#Sta/Elev= 30
       0 1811.97    18.8 1807.19    84.8 1788.99    94.2 1786.53   103.7 1784.39
   113.1 1782.68   141.4 1778.43   178.9 1772.48   197.4 1767.76   206.6  1766.6
   215.9 1766.69   221.2 1767.09   241.2 1768.69   252.9 1769.79   262.2 1770.92
   280.7 1773.55   317.7 1779.51   327.4 1781.52     337 1783.83   346.7  1785.2
   356.3 1786.28     395 1790.04   423.9 1793.43   443.2 1794.62   452.9 1794.92
   462.5 1795.15   481.8 1795.01   491.5 1796.66   530.1 1804.47     588 1815.48
#Mann= 3 , 0 , 0
       0      .1       0   221.2    .045       0   241.2      .1       0
Bank Sta=221.2,241.2
XS Rating Curve= 0 ,0
Exp/Cntr=0.3,0.1

Type RM Length L Ch R = 1 ,1221    ,280.3,277.2,273.8
XS GIS Cut Line= 4
     1940730.264      408772.093     1940971.149      408765.582
     1941094.847      408754.731      1941296.67      408654.905
#Sta/Elev= 30
       0 1823.05    57.8 1804.24    86.8 1795.43     135 1780.34   144.6 1777.86
   154.2 1776.27   163.9 1775.33   260.1 1768.03   269.6 1766.97   279.2 1765.21
   288.7 1762.68   296.7 1761.23   298.3 1760.94   307.8 1761.77   316.7 1763.43
   326.9 1764.55   374.9 1765.35   414.1 1766.44   423.9 1766.88   433.7 1768.02
   443.5 1771.04   453.2 1776.01     463 1780.33   472.8 1782.72   502.2 1787.53
     512 1789.34   521.8 1791.64   531.6 1794.47   570.7  1806.6   590.3 1812.31
#Mann= 3 , 0 , 0
       0      .1       0   296.7    .045       0   316.7      .1       0
Bank Sta=296.7,316.7
XS Rating Curve= 0 ,0
Exp/Cntr=0.3,0.1

Type RM Length L Ch R = 1 ,943.8   ,413.6,426.7,436.5
XS GIS Cut Line= 3
     1940799.708      408958.725     1941107.868      409019.488
     1941466.229      408940.365
#Sta/Elev= 30
       0 1799.34    78.5 1776.51    88.3  1773.8     108 1768.96   137.4 1762.33
   147.2 1760.72     157 1760.07   166.9 1760.05   235.6 1761.13   314.1  1761.2
   323.8 1760.99   333.4 1759.71   343.9 1757.52   352.7 1756.57   363.9 1757.17
   381.7 1758.82     401    1760   410.7 1761.34   420.3 1763.38   439.6 1767.87
     459 1771.92   468.6 1773.69   478.3 1775.23   507.2 1779.49   526.6 1783.03
   545.9 1787.21   565.2 1791.83   603.8 1801.91   632.8 1810.46   681.1 1822.62
#Mann= 3 , 0 , 0
       0      .1       0   343.9    .045       0   363.9      .1       0
Bank Sta=343.9,363.9
XS Rating Curve= 0 ,0
Exp/Cntr=0.3,0.1

Type RM Length L Ch R = 1 ,517.1   ,224.9,217.7,202.2
XS GIS Cut Line= 4
     1940967.706      409316.465     1941145.657      409383.739
     1941232.463       409396.76     1941540.622      409338.166
#Sta/Elev= 30
       0 1775.85    28.5 1768.82    66.6 1758.24    76.1    1756    85.6  1754.3
    95.1 1753.42   104.6 1753.16   152.2 1752.46   180.7 1752.49     200 1751.94
   209.8 1751.22   219.4 1749.93   229.3 1749.48   239.4 1749.86   248.8 1750.99
   258.5 1752.43   268.3 1753.46   297.6  1756.2   307.4 1756.93   317.2 1757.38
   346.6 1757.51     376 1756.66   385.8  1756.6   464.3 1756.62   474.1 1757.05
   483.9 1758.42   523.1 1765.83   572.1 1776.02   581.9 1778.22   591.7  1780.7
#Mann= 3 , 0 , 0
       0      .1       0   219.4    .045       0   239.4      .1       0
Bank Sta=219.4,239.4
XS Rating Curve= 0 ,0
Exp/Cntr=0.3,0.1

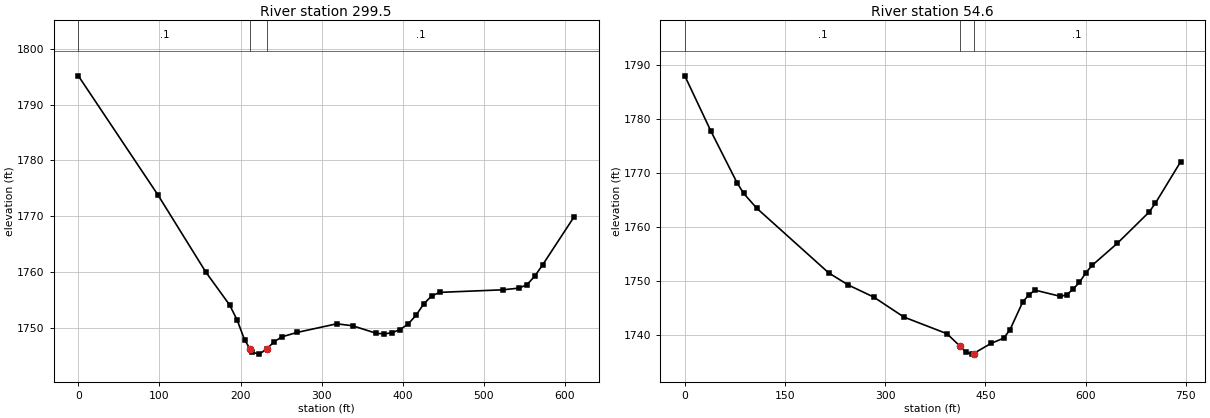
Type RM Length L Ch R = 1 ,299.5   ,246.1,244.8,242.1
XS GIS Cut Line= 4
     1940944.529      409500.753      1941124.65      409549.581
      1941197.35       409538.73     1941522.871      409406.352
#Sta/Elev= 30
       0 1795.16    98.2 1773.82   157.2 1760.02   186.6 1754.12   195.8 1751.45
     205 1747.89   212.2 1746.15   214.2 1745.67   223.4 1745.32   232.2 1746.26
   241.8 1747.56   250.9 1748.41   269.9 1749.21   318.7 1750.75   338.2  1750.4
   367.5 1749.05   377.3 1748.94     387 1749.16   396.8 1749.72   406.6 1750.68
   416.3 1752.25   426.1 1754.33   435.8 1755.74   445.6 1756.38   523.7 1756.84
   543.2 1757.14     553 1757.72   562.7 1759.24   572.5 1761.28   611.5 1769.93
#Mann= 3 , 0 , 0
       0      .1       0   212.2    .045       0   232.2      .1       0
Bank Sta=212.2,232.2
XS Rating Curve= 0 ,0
Exp/Cntr=0.3,0.1

Type RM Length L Ch R = 1 ,54.6    ,49.5,54.6,60.6
XS GIS Cut Line= 5
     1940948.174      409596.413     1941202.081      409670.197
     1941308.418      409694.069     1941436.456      409661.517
     1941581.855      409474.885
#Sta/Elev= 30
       0 1788.03    39.2 1777.74    78.3 1768.18    88.1 1766.23   107.7 1763.48
   215.4 1751.49   244.8 1749.24   282.6 1747.02     328  1743.3   392.3 1740.22
   412.1 1737.89   420.6  1736.8     430 1736.43   432.1 1736.53   458.3 1738.42
   477.2 1739.38   486.6 1740.92   505.5 1746.03     515 1747.45   524.4 1748.29
   562.3 1747.14   571.8 1747.44   581.2  1748.5   590.7 1749.73   600.1  1751.5
   609.6 1752.88   647.5 1756.99   694.8 1762.75   704.2 1764.39   742.1 1772.09
#Mann= 3 , 0 , 0
       0      .1       0   412.1    .045       0   432.1      .1       0
Bank Sta=412.1,432.1
XS Rating Curve= 0 ,0
Exp/Cntr=0.3,0.1

Chan Stop Cuts=-1
Use User Specified Reach Order=0
Composite Channel Slope=5